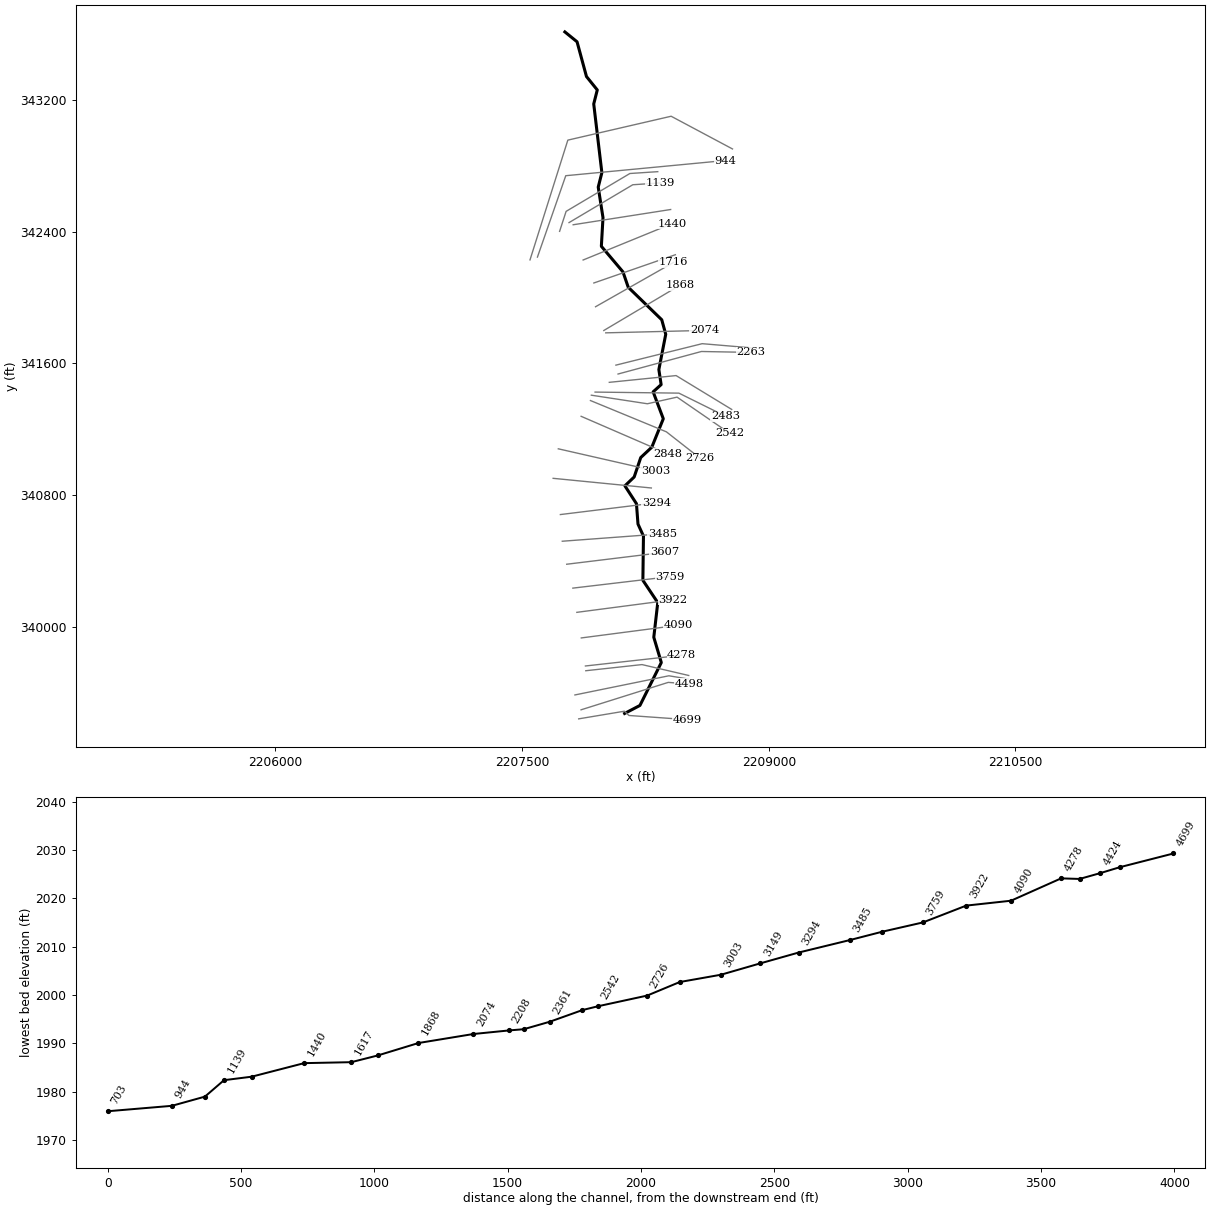
--- WILEYRN.prj (project) ---

Proj Title=WILEYRN
Current Plan=p01
Default Exp/Contr=0.3,0.1
English Units
Geom File=g02
Flow File=f01
Plan File=p01
BEGIN DESCRIPTION:
Stream Name- Wiley Run
Flood Zone: Zone A
Greenbrier County, WV
County-Wide Study
WVDHSEM-2018-3, Flood Risk Project
HEC-RAS Version: 5.0.7
General Notes:
For the Hydrology Regression was used.
END DESCRIPTION:
DSS Export Rating Curves= 0
DSS Export Rating Curve Sorted= 0
DSS Export Volume Flow Curves= 0
DXF OffsetX= 0
DXF OffsetY= 0
DXF ScaleX= 0
DXF ScaleY= 0

--- WILEYRN.p01 (plan) ---

Plan Title=Floodplain
Program Version=5.07
Short Identifier=Floodplain
Geom File=g02
Flow File=f01
Subcritical Flow
K Sum by GR= 0
Std Step Tol= 0.01
Critical Tol= 0.01
Num of Std Step Trials= 20
Max Error Tol= 0.3
Flow Tol Ratio= 0.001
Split Flow NTrial= 30
Split Flow Tol= 0.02
Split Flow Ratio= 0.02
Log Output Level= 0
Friction Slope Method= 1
Unsteady Friction Slope Method= 2
Unsteady Bridges Friction Slope Method= 1
Parabolic Critical Depth
Global Vel Dist= 0 , 0 , 0
Global Log Level= 0
CheckData=True
Encroach Param=-1 ,0,0, 0
Computation Interval=1MIN
Output Interval=1HOUR
Instantaneous Interval=1HOUR
Mapping Interval=1HOUR
Computation Time Step Use Courant=        0
Computation Time Step Use Time Series=    0
Computation Time Step Count To Double=0
Computation Time Step Max Doubling=0
Computation Time Step Max Halving=0
Computation Time Step Residence Courant=0
Run HTab= 0
Run UNet= 0
Run Sediment= 0
Run PostProcess= 0
Run WQNet= 0
Run RASMapper=-1
UNET Theta= 1
UNET Theta Warmup= 1
UNET ZTol= 0.02
UNET ZSATol= 0.02
UNET MxIter= 20
UNET Max Iter WO Improvement= 0
UNET MaxInSteps= 0
UNET DtIC= 0
UNET DtMin= 0
UNET MaxCRTS= 20
UNET WFStab= 2
UNET SFStab= 1
UNET WFX= 1
UNET SFX= 1
UNET 1D Methodology=Finite Difference
UNET DSS MLevel= 4
UNET Pardiso=0
UNET DZMax Abort= 100
UNET Use Existing IB Tables=-1
UNET Froude Reduction=False
UNET Froude Limit= 0.8
UNET Froude Power= 4
UNET D1 Cores= 0
UNET D2 Coriolis=0
UNET D2 Cores= 0
UNET D2 Theta= 1
UNET D2 Theta Warmup= 1
UNET D2 Z Tol= 0.01
UNET D2 Volume Tol= 0.01
UNET D2 Max Iterations= 20
UNET D2 Equation= 0
UNET D2 RampUpFraction=0.1
UNET D2 TimeSlices= 1
UNET D2 BCVolumeCheck=0
UNET D1D2 MaxIter= 0
UNET D1D2 ZTol=0.01
UNET D1D2 QTol=0.1
UNET D1D2 MinQTol=1
Write IC File= 0
Write IC File at Fixed DateTime=0
Write IC File at Sim End=0
Echo Input=False
Echo Parameters=False
Echo Output=False
Write Detailed= 0
HDF Write Warmup=0
HDF Write Time Slices=0
HDF Flush=0
HDF Face Node Velocities=0
HDF Compression= 1
HDF Chunk Size= 1
HDF Spatial Parts= 1
HDF Use Max Rows=0
HDF Fixed Rows= 1
Calibration Method= 0
Calibration Iterations= 20
Calibration Max Change=0.05
Calibration Tolerance=0.2
Calibration Maximum=1.5
Calibration Minimum=0.5
Calibration Optimization Method= 1
WQ AD Non Conservative
WQ ULTIMATE=-1
WQ Max Comp Step=1HOUR
WQ Output Interval=15MIN
WQ Output Selected Increments= 0
WQ Output face flow=0
WQ Output face velocity=0
WQ Output face area=0
WQ Output face dispersion=0
WQ Output cell volume=0
WQ Output cell surface area=0
WQ Output cell continuity=0
WQ Output cumulative cell continuity=0
WQ Output face conc=0
WQ Output face dconc_dx=0
WQ Output face courant=0
WQ Output face peclet=0
WQ Output face adv mass=0
WQ Output face disp mass=0
WQ Output cell mass=0
WQ Output cell source sink temp=0
WQ Output nsm pathways=0
WQ Output nsm derived pathways=0
WQ Output MaxMinRange=-1
WQ Daily Max Min Mean=-1
WQ Daily Range=0
WQ Daily Time=0
WQ Create Restart=0
WQ Fixed Restart=0
WQ System Summary=0
WQ Write To DSS=0
WQ Use Fixed Temperature=0
Sorting and Armoring Iterations= 10
XS Update Threshold= 0.02
Bed Roughness Predictor= 0
Hydraulics Update Threshold= 0.02
Energy Slope Method= 1
Volume Change Method= 1
Sediment Retention Method= 0
XS Weighting Method= 0
Number of US Weighted Cross Sections= 1
Number of DS Weighted Cross Sections= 1
Upstream XS Weight=0
Main XS Weight=1
Downstream XS Weight=0
Number of DS XS's Weighted with US Boundary= 1
Upstream Boundary Weight= 1
Weight of XSs Associated with US Boundary= 0
Number of US XS's Weighted with DS Boundary= 1
Downstream Boundary Weight= 0.5
Weight of XSs Associated with DS Boundary= 0.5
Percentile Method= 0
Sediment Output Level= 3
Mass or Volume Output= 0
Output Increment Type= 1
Profile and TS Output Increment= 1
XS Output Flag= 0
XS Output Increment= 10
Write Gradation File= 0
Read Gradation Hotstart= 0
Write HDF5 File= 1
Write Binary Output= 1
Write DSS Sediment File= 0
SV Curve= 0
Specific Gage Flag= 0

--- WILEYRN.f01 (steady flow) ---

Flow Title=Flow
Program Version=5.07
Number of Profiles= 6
Profile Names=f1p,f10p,f4p,f2p,f02p,f1pplus
River Rch & RM=WILEYRN,Main            ,4699
     552     291     388     467     772     817
River Rch & RM=WILEYRN,Main            ,2483
     667     354     470     565     929     986
River Rch & RM=WILEYRN,Main            ,2074
     823     441     583     699    1140    1220
Boundary for River Rch & Prof#=WILEYRN,Main            , 1
Up Type= 0
Dn Type= 3
Dn Slope=0.00542
Boundary for River Rch & Prof#=WILEYRN,Main            , 2
Up Type= 0
Dn Type= 3
Dn Slope=0.00542
Boundary for River Rch & Prof#=WILEYRN,Main            , 3
Up Type= 0
Dn Type= 3
Dn Slope=0.00542
Boundary for River Rch & Prof#=WILEYRN,Main            , 4
Up Type= 0
Dn Type= 3
Dn Slope=0.00542
Boundary for River Rch & Prof#=WILEYRN,Main            , 5
Up Type= 0
Dn Type= 3
Dn Slope=0.00542
Boundary for River Rch & Prof#=WILEYRN,Main            , 6
Up Type= 0
Dn Type= 3
Dn Slope=0.00542
DSS Import GetInterval= 0
DSS Import GetPeak= 0
DSS Import FillOption= 0

--- WILEYRN.g02 (geometry) ---

Geom Title=Wiley Run
Program Version=5.07

River Reach=WILEYRN         ,Main
Reach XY= 30
     2208123.462      339471.153     2208216.667      339519.957
     2208346.601      339780.863     2208300.849      339934.618
     2208324.982      340145.3852208234.50976459340280.982666801
     2208238.058      340549.735      2208204.76      340622.906
     2208195.374      340746.875     2208125.195      340855.271
     2208181.599      340909.216     2208221.498      341027.322
     2208288.841      341090.364     2208358.664      341263.306
2208296.94103902341426.9472040372208345.51696578341470.896852057
     2208331.697      341562.327     2208373.522      341777.021
     2208349.286       341865.22     2208145.425      342063.066
     2208113.455      342156.402     2207981.983      342312.057
     2207991.985      342486.122     2207962.987      342671.823
     2207985.116      342759.877     2207935.627      343177.514
     2207957.215      343262.805     2207891.514      343344.268
     2207834.194      343555.642     2207760.146      343615.689

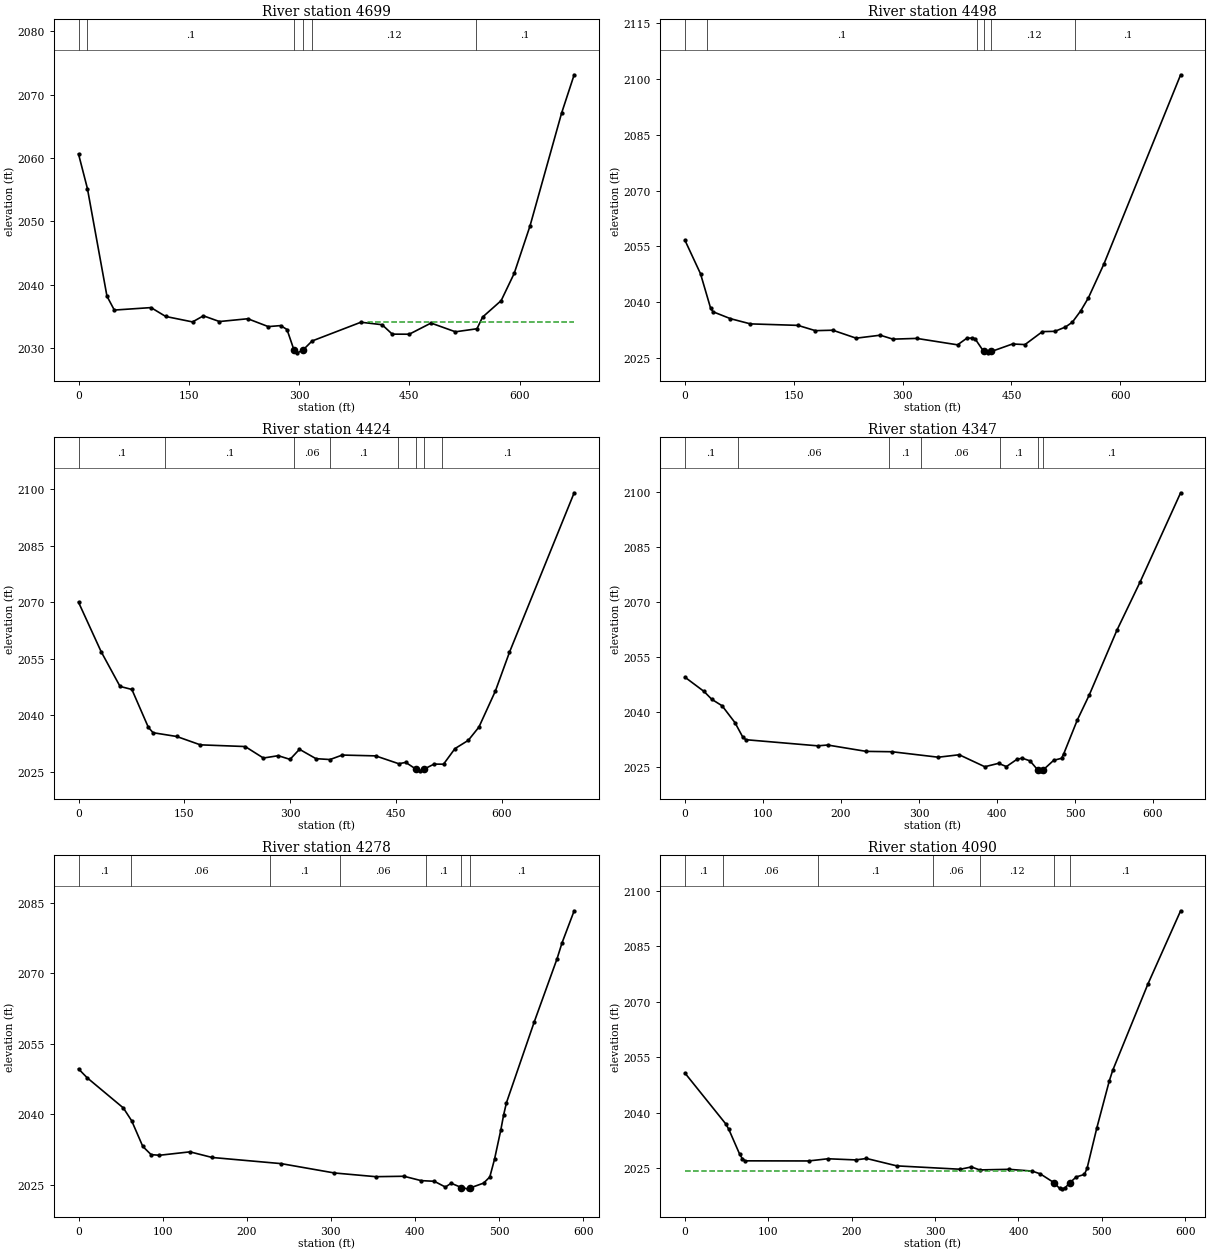
Type RM Length L Ch R = 1 ,4699    ,197.4,201.4,207.2
XS GIS Cut Line= 4
2207844.13434286339438.4230823962208122.78848483   339485.020765
2208149.81514074339458.9260627422208503.02557488339433.763314136
#Sta/Elev= 30
       0 2060.64    12.1 2055.19    38.7  2038.2    48.7 2036.01    98.6  2036.4
   118.6    2035   155.1 2034.14   169.9  2035.1   191.7  2034.2   230.3 2034.64
   258.1  2033.4   274.9 2033.56   283.6 2032.94     293 2029.74   297.8 2029.26
   305.6 2029.73   317.7 2031.13   384.1 2034.09   412.9  2033.7   426.8 2032.21
   449.9  2032.2   479.5 2033.96   512.7 2032.58     542 2033.06   549.6  2034.9
   574.9  2037.5   592.6 2041.79   614.1 2049.27   657.1 2067.09   674.2 2073.14
#Mann= 6 ,-1 , 0
       0      .1       0   11.65      .1       0     293    .045       0
   305.6      .1       0   317.7     .12       0  540.14      .1       0
#XS Ineff= 2 , 0
                          393.62         2034.07
Permanent Ineff=
       F       F
Bank Sta=293,305.6
XS Rating Curve= 0 ,0
Exp/Cntr=0.3,0.1

Type RM Length L Ch R = 1 ,4498    ,74.3,73.2,73.7
XS GIS Cut Line= 3
2207858.57962446339493.408347868 2208388.8612525 339660.22805159
2208515.60694918339649.976561417
#Sta/Elev= 30
       0 2056.65    21.4 2047.68    35.2  2038.5    38.6 2037.46    62.7  2035.6
    90.2  2034.2   155.7  2033.8   179.7 2032.38   203.7  2032.5   235.9 2030.36
   269.1 2031.16   286.6  2030.1   319.4  2030.3   375.7 2028.57   388.4 2030.35
     396  2030.4   399.8  2030.2   411.6 2026.81     417 2026.42   422.4 2026.79
   451.4  2028.8   468.6 2028.64   492.6 2032.12   509.8  2032.2   524.4 2033.36
   533.9 2034.66   545.4  2037.7   555.9 2041.17   577.3 2050.26   683.1 2101.14
#Mann= 6 ,-1 , 0
       0      .1       0   30.17      .1       0  402.26     .12       0
   411.6    .045       0   422.4     .12       0   538.2      .1       0
Bank Sta=411.6,422.4
XS Rating Curve= 0 ,0
Exp/Cntr=0.3,0.1

Type RM Length L Ch R = 1 ,4424    ,78.3,77.3,72.9
XS GIS Cut Line= 3
2207821.30147838 339583.80785212 2208392.5890671339700.302058629
2208510.94718092339680.731031936
#Sta/Elev= 30
       0 2069.96    32.1 2056.83    58.9 2047.61    75.7  2046.8    99.1 2036.73
   105.8 2035.32   139.3 2034.32   172.8  2032.1   236.4 2031.65   262.2  2028.6
   283.3 2029.22     300 2028.24   313.4 2030.92   336.8 2028.43   356.7  2028.2
   374.1 2029.39   421.4 2029.17   454.2 2027.09   464.1 2027.44   479.1 2025.59
   484.2  2025.2   490.2 2025.67   504.3 2026.99   517.7 2026.96   533.9  2031.1
   552.8 2033.29   567.9 2036.81   591.3  2046.4   611.2 2056.66     703 2099.01
#Mann= 8 ,-1 , 0
       0      .1       0  122.57      .1       0   306.3     .06       0
  357.05      .1       0  453.05     .12       0   479.1    .045       0
   490.2     .12       0  516.01      .1       0
#XS Ineff= 1 ,-1
  253.53  309.86 2029.06
Permanent Ineff=
       F
Bank Sta=479.1,490.2
XS Rating Curve= 0 ,0
Exp/Cntr=0.3,0.1

Type RM Length L Ch R = 1 ,4347    ,67.3,69.2,70.3
XS GIS Cut Line= 3
2207887.47018768339731.0565291482208229.17568326339768.424509674
2208513.27706505339702.165965934
#Sta/Elev= 30
       0  2049.5    24.5 2045.61    34.4 2043.47    47.6 2041.72    64.1 2037.13
      74 2033.23      78 2032.48   170.2 2030.81   182.9 2031.03   232.4  2029.3
   265.5  2029.2   324.8 2027.71   351.6 2028.38   384.4 2025.12     402 2026.04
   412.1 2025.16   425.5 2027.12   432.3 2027.46   442.4 2026.71   452.1  2024.3
   455.9    2024   459.2 2024.24   472.7 2026.86   482.8 2027.42   485.5 2028.57
     503 2037.83   518.3 2044.64   553.8 2062.29   583.7 2075.51   635.5 2099.73
#Mann= 7 ,-1 , 0
       0      .1       0   67.47     .06       0  261.95      .1       0
  303.13     .06       0  404.07      .1       0   452.1    .045       0
   459.2      .1       0
#XS Ineff= 2 , 0
          350.79  2028.3
Permanent Ineff=
       F       F
Bank Sta=452.1,459.2
XS Rating Curve= 0 ,0
Exp/Cntr=0.3,0.1

Type RM Length L Ch R = 1 ,4278    ,187.6,188,187.1
XS GIS Cut Line= 2
2207885.14030355339759.9470923622208470.79257971339825.066318801
#Sta/Elev= 30
       0 2049.67    10.4 2047.76    53.3 2041.35    63.2 2038.62    76.4 2033.16
    86.3 2031.41    96.2 2031.27   132.5    2032   158.9  2030.8     241 2029.49
   304.2  2027.5   353.4 2026.71   386.9  2026.8   407.3 2025.87     423 2025.73
   436.2  2024.5     443 2025.31   455.22024.404   462.6 2024.12   465.9 2024.33
   481.6 2025.34     489 2026.65   494.6 2030.42     502 2036.58   505.5 2039.92
   508.8 2042.47   541.8 2059.66   568.9  2073.1   574.8 2076.48   589.3 2083.35
#Mann= 7 ,-1 , 0
       0      .1       0   62.68     .06       0     228      .1       0
  310.48     .06       0  413.59      .1       0   455.2    .045       0
   465.9      .1       0
Bank Sta=455.2,465.9
XS Rating Curve= 0 ,0
Exp/Cntr=0.3,0.1

Type RM Length L Ch R = 1 ,4090    ,167.9,167.9,165.3
XS GIS Cut Line= 2
2207859.97755494339930.494610692 2208449.4541598340007.439387574
#Sta/Elev= 30
       0 2050.75      49 2037.01    52.6 2035.55    65.5  2028.9    68.9 2027.61
    72.2 2027.06   148.3 2027.03   171.4 2027.62   204.8 2027.31   217.7  2027.7
   254.1  2025.7   330.2 2024.79   343.5 2025.41   353.5 2024.61   388.7 2024.77
   416.3  2024.3   426.2 2023.54   442.7 2021.15   449.4  2019.6   452.7  2019.5
     456  2019.8   461.8 2021.17   469.2 2022.71   479.1 2023.39   482.3 2025.05
     494 2035.96   508.9 2048.62     513 2051.47   555.2 2074.77   594.5 2094.58
#Mann= 7 ,-1 , 0
       0      .1       0   45.57     .06       0  160.11      .1       0
  296.92     .06       0  353.41     .12       0   442.7    .045       0
   461.8      .1       0
#XS Ineff= 2 , 0
          416.64  2024.3
Permanent Ineff=
       F       F
Bank Sta=442.7,461.8
XS Rating Curve= 0 ,0
Exp/Cntr=0.3,0.1

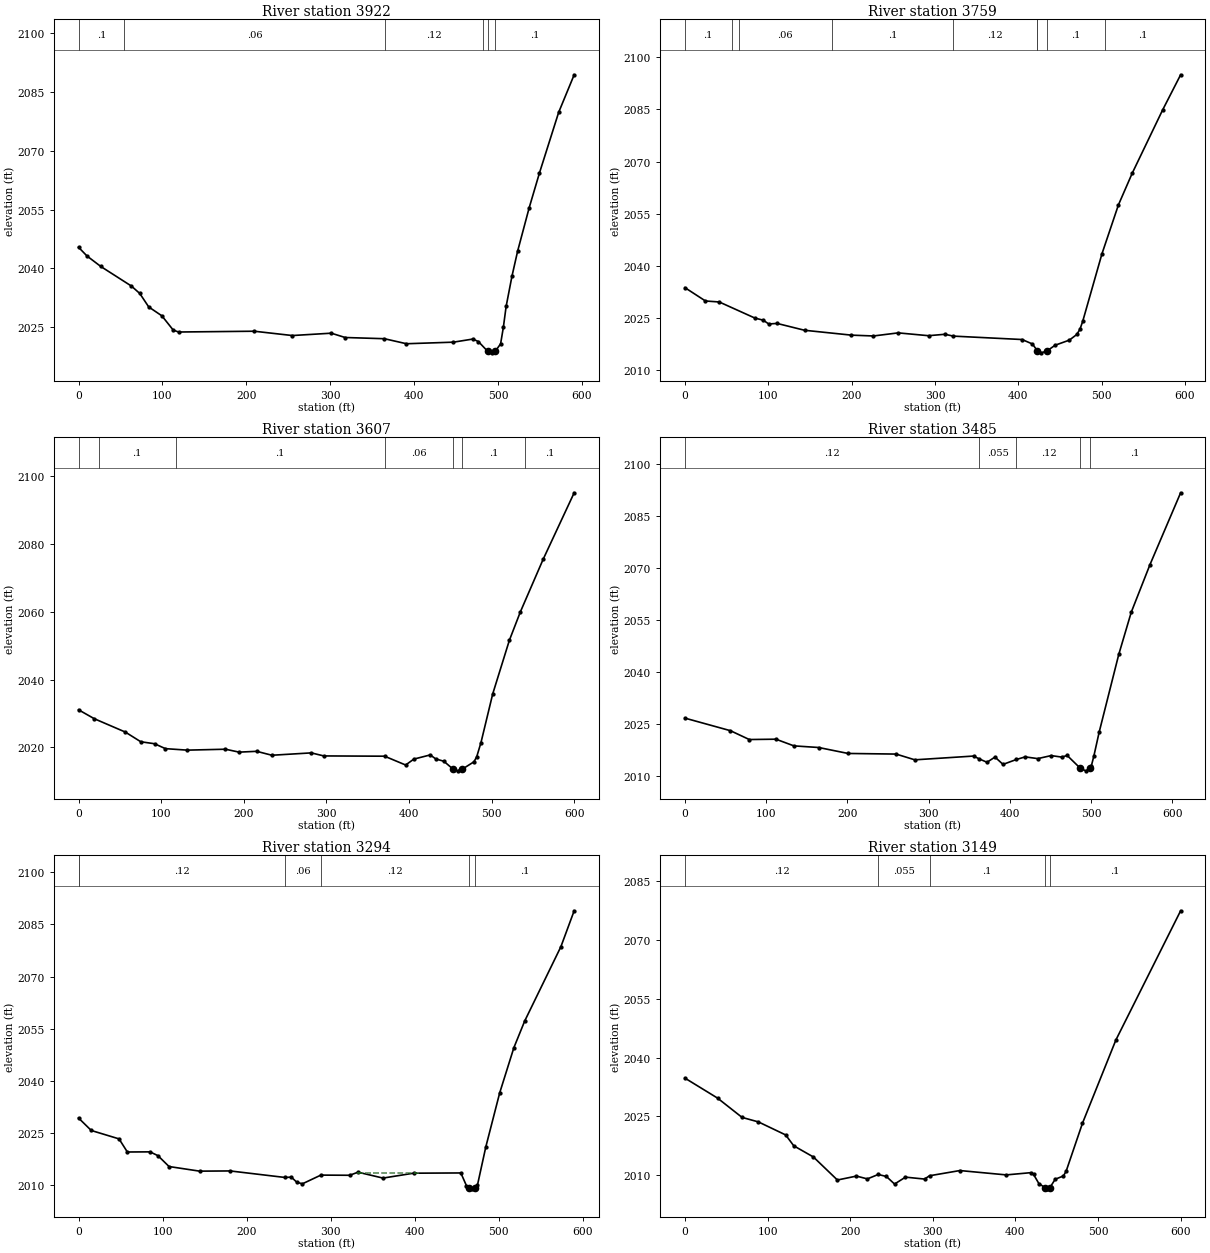
Type RM Length L Ch R = 1 ,3922    ,161.4,162.5,160.2
XS GIS Cut Line= 2
2207832.95089903340086.1308705892208418.79620337340162.785800436
#Sta/Elev= 30
       0 2045.41    10.1 2043.18    26.6  2040.5      63 2035.52      73 2033.63
    83.7 2030.19    99.4 2027.92   112.9 2024.29   119.3  2023.8   209.5    2024
   254.9  2022.9   301.3  2023.5   317.8  2022.4   364.6 2022.09   390.9 2020.81
   446.8 2021.21     470    2022   476.6 2021.37   487.5 2018.93     493 2018.49
   496.8 2018.91   503.1 2020.77   506.4 2024.98   509.7 2030.32   516.7 2038.07
   523.4 2044.41   537.2 2055.49   549.4 2064.32   572.3 2079.78   590.8 2089.37
#Mann= 6 ,-1 , 0
       0      .1       0   54.46     .06       0  365.52     .12       0
   481.9      .1       0   487.5    .045       0   496.8      .1       0
Bank Sta=487.5,496.8
XS Rating Curve= 0 ,0
Exp/Cntr=0.3,0.1

Type RM Length L Ch R = 1 ,3759    ,151.5,152,151.6
XS GIS Cut Line= 2
2207808.72010408340233.3795476172208399.32169077340303.220954864
#Sta/Elev= 30
       0 2033.75    24.6 2029.92    41.1 2029.64      84    2025    93.9  2024.4
   100.5 2023.31   110.5 2023.47   143.5  2021.5   199.7  2020.1   226.1 2019.86
   255.8 2020.75   292.2 2019.94     312 2020.35   321.9 2019.82   404.5 2018.84
   416.9 2017.55   422.5 2015.71   422.8 2015.64   427.6 2015.01   434.6 2015.59
   444.1  2017.2   461.2 2018.67   470.1 2020.29   473.9 2021.79   477.2 2024.06
   500.3 2043.49   520.1 2057.58   536.6 2066.66     573 2084.82   594.7 2094.98
#Mann= 9 ,-1 , 0
       0      .1       0    55.9      .1       0   64.55     .06       0
  176.16      .1       0   321.9     .12       0   422.5    .055       0
   422.8    .045       0   434.6      .1       0  504.01      .1       0
#XS Ineff= 2 , 0
          312.04 2020.27
Permanent Ineff=
       F       F
Bank Sta=422.8,434.6
XS Rating Curve= 0 ,0
Exp/Cntr=0.3,0.1

Type RM Length L Ch R = 1 ,3607    ,122.6,122.5,122.1
XS GIS Cut Line= 2
2207771.35879796340378.6569526672208366.94990692340451.260195849
#Sta/Elev= 30
       0 2031.12    19.2 2028.47    56.6 2024.55    75.4 2021.68      92  2021.1
   105.2 2019.65   131.6 2019.21   177.9 2019.48   194.4 2018.62   215.7 2018.86
   234.1  2017.7   281.8  2018.4   296.9  2017.5   370.5 2017.42     396 2014.82
   405.9 2016.56   425.8  2017.8   432.4 2016.62   442.3 2015.92   453.3 2013.62
   458.8  2013.1   464.6  2013.6   478.7 2015.77     482 2017.22   487.2 2021.45
   501.4  2035.8   521.6 2051.65   534.8 2059.97   562.4  2075.5     600 2095.16
#Mann= 7 ,-1 , 0
       0      .1       0   24.22      .1       0  117.84      .1       0
   370.5     .06       0   453.3    .045       0   464.6      .1       0
  540.24      .1       0
Bank Sta=453.3,464.6
XS Rating Curve= 0 ,0
Exp/Cntr=0.3,0.1

Type RM Length L Ch R = 1 ,3485    ,190.2,190.8,191.1
XS GIS Cut Line= 2
2207744.41530208340518.5573651522208353.03627535340563.792838797
#Sta/Elev= 30
       0 2026.58      56 2022.95    79.2  2020.4     112  2020.5   134.1 2018.57
   164.6  2018.1   200.8 2016.38     260  2016.2     283 2014.54   355.4 2015.63
     362 2014.84   371.9 2013.83   381.7 2015.34   391.6 2013.22   408.1 2014.64
   418.9 2015.39   434.4 2014.89   450.8 2015.76     464 2015.33   470.6  2015.8
     487 2012.05   493.6 2011.36   498.6 2012.05   500.2 2012.63   503.5 2015.67
     510 2022.55   534.1 2044.96   549.5 2057.17   572.6 2070.94   610.3 2091.66
#Mann= 5 ,-1 , 0
       0     .12       0     362    .055       0   408.1     .12       0
     487    .045       0   498.6      .1       0
Bank Sta=487,498.6
XS Rating Curve= 0 ,0
Exp/Cntr=0.3,0.1

Type RM Length L Ch R = 1 ,3294    ,144.5,144.7,143.8
XS GIS Cut Line= 2
2207732.76588143340680.7173006132208318.03277494340752.477731823
#Sta/Elev= 30
       0 2029.22    15.2 2025.62    48.2  2023.2    58.1 2019.42    85.1 2019.46
    94.5 2018.36   107.7 2015.23     144  2013.9   180.4 2013.96   245.9 2012.07
   253.1 2012.19   259.8 2010.67   266.4 2010.26   288.3 2012.76   322.6 2012.71
   332.5  2013.6   362.2  2011.9   398.6 2013.31   454.8 2013.38   461.4 2009.74
   464.7 2009.11     468  2008.8   471.9 2009.06   474.6 2009.92   484.5 2020.89
     501 2036.45   517.9  2049.5   530.8  2057.2   573.8 2078.59   589.6 2088.95
#Mann= 6 ,-1 , 0
       0      .1       0    1.04     .12       0   245.9     .06       0
   288.3     .12       0   464.7    .045       0   471.9      .1       0
#XS Ineff= 1 ,-1
  331.52  404.472013.413
Permanent Ineff=
       F
Bank Sta=464.7,471.9
XS Rating Curve= 0 ,0
Exp/Cntr=0.3,0.1

Type RM Length L Ch R = 1 ,3149    ,145.3,146.9,147.1
XS GIS Cut Line= 2
2207688.87292351 340901.046520662208285.99102314340842.310031985
#Sta/Elev= 30
       0 2034.75    39.4 2029.67    69.1 2024.75    88.9  2023.6   121.9 2020.28
   131.7 2017.51   155.5 2014.66   184.5  2008.8   207.6  2009.8   220.8 2009.08
   233.9 2010.21   243.8  2009.7   253.7 2007.77   266.9 2009.53     290 2009.04
     296 2009.88   332.8 2011.21   388.9  2010.1   418.6 2010.67   421.9 2010.25
   428.4 2007.89   435.6 2006.89   438.3 2006.55   441.6 2006.83   448.2    2009
   458.1 2009.83   461.4 2011.04   481.2 2023.28   521.6 2044.46     600 2077.39
#Mann= 5 ,-1 , 0
       0     .12       0   233.9    .055       0     296      .1       0
   435.6    .045       0   441.6      .1       0
Bank Sta=435.6,441.6
XS Rating Curve= 0 ,0
Exp/Cntr=0.3,0.1

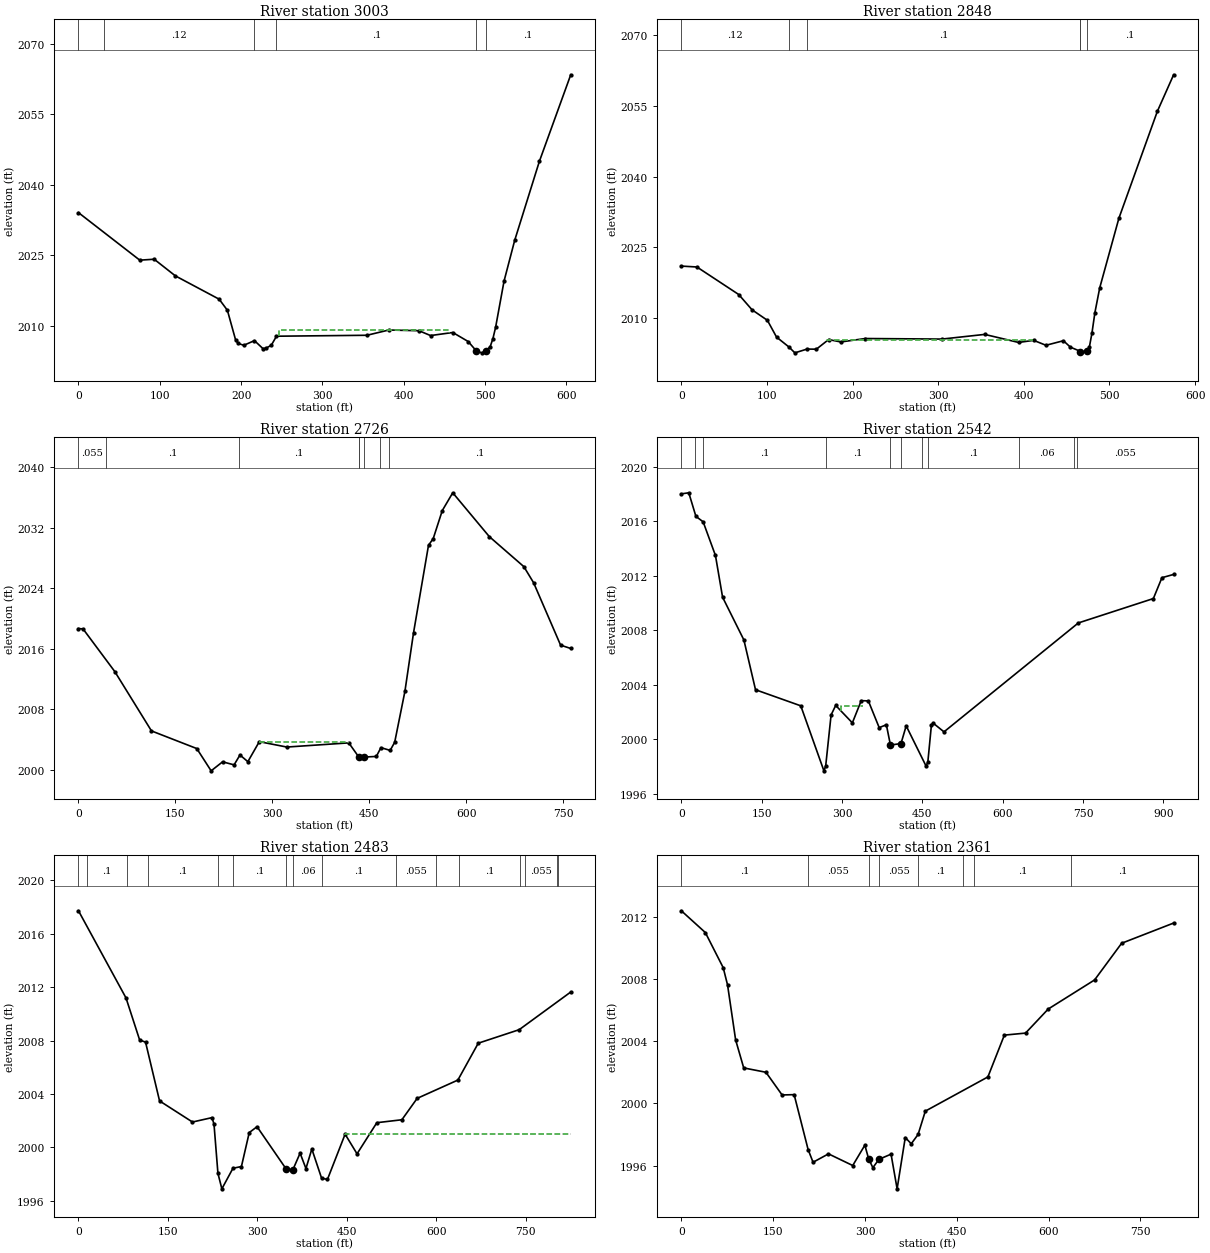
Type RM Length L Ch R = 1 ,3003    ,156.8,154.7,153.6
XS GIS Cut Line= 2
2207720.18450713341080.5254173542208310.40433286340946.032397069
#Sta/Elev= 30
       0 2034.06    75.4 2023.94    93.1 2024.14   119.2 2020.59     173 2015.63
   183.1 2013.28   193.2 2006.97   196.6  2006.2   203.3 2005.82   216.4 2006.81
   226.9  2005.1   230.5 2005.21     237  2005.8   243.5 2007.75   354.7 2007.95
   381.6 2009.07   418.7 2008.92   432.9 2007.89   460.3 2008.54   479.2 2006.62
   489.3  2004.6   495.9 2004.21   500.7 2004.56   506.2  2005.5   509.6 2007.23
   512.9 2009.63   523.3 2019.49   536.4 2028.17   566.7 2044.96   605.3 2063.41
#Mann= 6 ,-1 , 0
       0     .06       0   31.59     .12       0   216.4    .055       0
   243.5      .1       0   489.3    .045       0   500.7      .1       0
#XS Ineff= 1 ,-1
  246.98  455.79 2009.04
Permanent Ineff=
       F
Bank Sta=489.3,500.7
XS Rating Curve= 0 ,0
Exp/Cntr=0.3,0.1

Type RM Length L Ch R = 1 ,2848    ,122,122.1,121.9
XS GIS Cut Line= 2
2207859.04560129341278.0995915942208386.52228793341049.527685404
#Sta/Elev= 30
       0 2021.05    18.2 2020.86      67 2015.04    82.6  2011.8   100.5 2009.58
   111.2 2006.03   125.5 2003.96   132.6  2002.7   146.9  2003.5   157.7 2003.47
     172 2005.51   186.3    2005   214.9 2005.73   304.3 2005.61   354.3  2006.6
   393.8  2004.9   411.5 2005.34   425.8  2004.3   446.2 2005.26   454.4  2003.9
   465.2 2003.08   466.1 2002.96   473.6 2003.03   476.6 2004.01   479.5 2006.83
     483 2011.23   488.6 2016.44     511 2031.17   555.9 2053.78   574.9 2061.52
#Mann= 6 ,-1 , 0
       0     .12       0   125.5    .055       0   146.9      .1       0
   465.2    .055       0   466.1    .045       0   473.6      .1       0
#XS Ineff= 1 ,-1
   169.6  411.152005.332
Permanent Ineff=
       F
Bank Sta=466.1,473.6
XS Rating Curve= 0 ,0
Exp/Cntr=0.3,0.1

Type RM Length L Ch R = 1 ,2726    ,181,184,187.5
XS GIS Cut Line= 3
2207915.69874225341374.0287440232208377.57056116341183.751191581
2208583.69673421341022.194590295
#Sta/Elev= 30
       0 2018.68     7.1 2018.63    56.2    2013   112.9 2005.17     183 2002.84
   205.2  1999.9   222.9 2001.09   240.7 2000.69   249.8 2001.99     262 2001.11
   279.7 2003.75   322.3 2003.04   418.1 2003.59   433.8  2001.7   441.9 2001.72
   460.7  2001.8   467.8 2002.96   482.1  2002.6   489.1 2003.67   504.9 2010.38
   518.3 2018.15   541.4 2029.67   548.7 2030.55   562.7 2034.25   578.9  2036.6
   635.4 2030.82   688.9 2026.85     704 2024.72   745.7 2016.49   761.4 2016.05
#Mann= 8 ,-1 , 0
       0    .055       0   43.08      .1       0  247.63      .1       0
  433.75    .055       0   433.8    .045       0   441.9      .1       0
   465.9    .055       0   480.7      .1       0
#XS Ineff= 1 ,-1
  279.01  417.23 2003.75
Permanent Ineff=
       F
Bank Sta=433.8,441.9
XS Rating Curve= 0 ,0
Exp/Cntr=0.3,0.1

Type RM Length L Ch R = 1 ,2542    ,59.6,59,58
XS GIS Cut Line= 4
2207921.03726391341406.6087270162208262.03328682341354.459143307
2208442.36547918341394.7885014712208763.18153603341174.136525105
#Sta/Elev= 30
       0 2018.02    13.9  2018.1    27.2 2016.37    40.7 2015.97    63.7  2013.5
      77 2010.44   116.8  2007.3   138.5 2003.65     223 2002.47   266.2  1997.7
   269.5 1998.05   279.6  2001.8   288.2  2002.5   319.3 2001.22   335.9 2002.85
   349.2 2002.83   369.4 2000.87   382.8 2001.08   390.41999.593   410.11999.701
   419.8    2001   456.8 1998.06   460.2 1998.33   466.9 2001.06   470.2  2001.2
   490.4 2000.56   741.2 2008.55   881.3 2010.34   897.3 2011.87   919.1 2012.11
#Mann= 11 ,-1 , 0
       0    .055       0    26.3      .1       0   39.98      .1       0
  270.21      .1       0   390.4    .045       0   410.1      .1       0
   449.5    .055       0  460.61      .1       0  630.55     .06       0
  733.44      .1       0  739.33    .055       0
#XS Ineff= 2 ,-1
   298.2  339.54 2002.48  470.01  515.22 2001.18
Permanent Ineff=
       F       F
Bank Sta=390.4,410.1
XS Rating Curve= 0 ,0
Exp/Cntr=0.3,0.1

Type RM Length L Ch R = 1 ,2483    ,119.8,121.9,123.6
XS GIS Cut Line= 3
2207943.72433086341425.4773213992208453.51397753 341419.09976136
2208736.47996472341279.031545246
#Sta/Elev= 30
       0 2017.71    79.7 2011.19   102.6 2008.04   112.5 2007.88     136 2003.48
   191.2  2001.9     224 2002.23   227.3 2001.74   233.9 1998.06   240.5  1996.9
   259.1 1998.44   273.3 1998.57   286.4 2001.11   299.5 2001.55   348.7 1998.36
   359.6 1998.33   371.7 1999.57   381.5 1998.42   391.4 1999.88   407.8 1997.69
   417.6 1997.61   447.2 2000.99   467.2 1999.52   500.4 2001.85   542.4 2002.07
     568 2003.67   636.3 2005.04   670.5  2007.8   739.1 2008.81   825.6 2011.63
#Mann= 16 ,-1 , 0
       0    .055       0   13.87      .1       0   82.22     .06       0
   117.1      .1       0   233.9    .055       0   259.1      .1       0
   348.7    .045       0   359.6     .06       0   408.9      .1       0
  532.46    .055       0  599.07      .1       0  638.44      .1       0
  741.28     .06       0  748.56    .055       0  802.08      .1       0
  803.47      .1       0
#XS Ineff= 2 , 0
                          446.84         2000.99
Permanent Ineff=
       F       F
Bank Sta=348.7,359.6
XS Rating Curve= 0 ,0
Exp/Cntr=0.3,0.1

Type RM Length L Ch R = 1 ,2361    ,97.1,97.9,98.2
XS GIS Cut Line= 3
2208030.27952629341484.7735916322208436.50580198341525.864051275
2208774.69006445341320.037505937
#Sta/Elev= 30
       0 2012.39    39.2 2010.99    68.4 2008.73    75.5 2007.62    88.7 2004.08
   101.9 2002.28   138.2    2002   164.6 2000.54   184.3 2000.56   207.1 1997.03
   215.2 1996.21   240.4 1996.75     280    1996   299.8 1997.31   305.9 1996.44
   312.9 1995.86   322.8  1996.4   342.6 1996.73   352.5  1994.5   365.8  1997.8
   375.6  1997.4   386.8    1998   398.6  1999.5   500.8  2001.7   527.7 2004.39
   562.3 2004.52   599.4 2006.07   675.1 2007.94   719.3  2010.3   804.2  2011.6
#Mann= 8 ,-1 , 0
       0      .1       0   207.1    .055       0   305.9    .045       0
   322.8    .055       0   386.8      .1       0  459.48    .055       0
  477.43      .1       0   636.8      .1       0
Bank Sta=305.9,322.8
XS Rating Curve= 0 ,0
Exp/Cntr=0.3,0.1

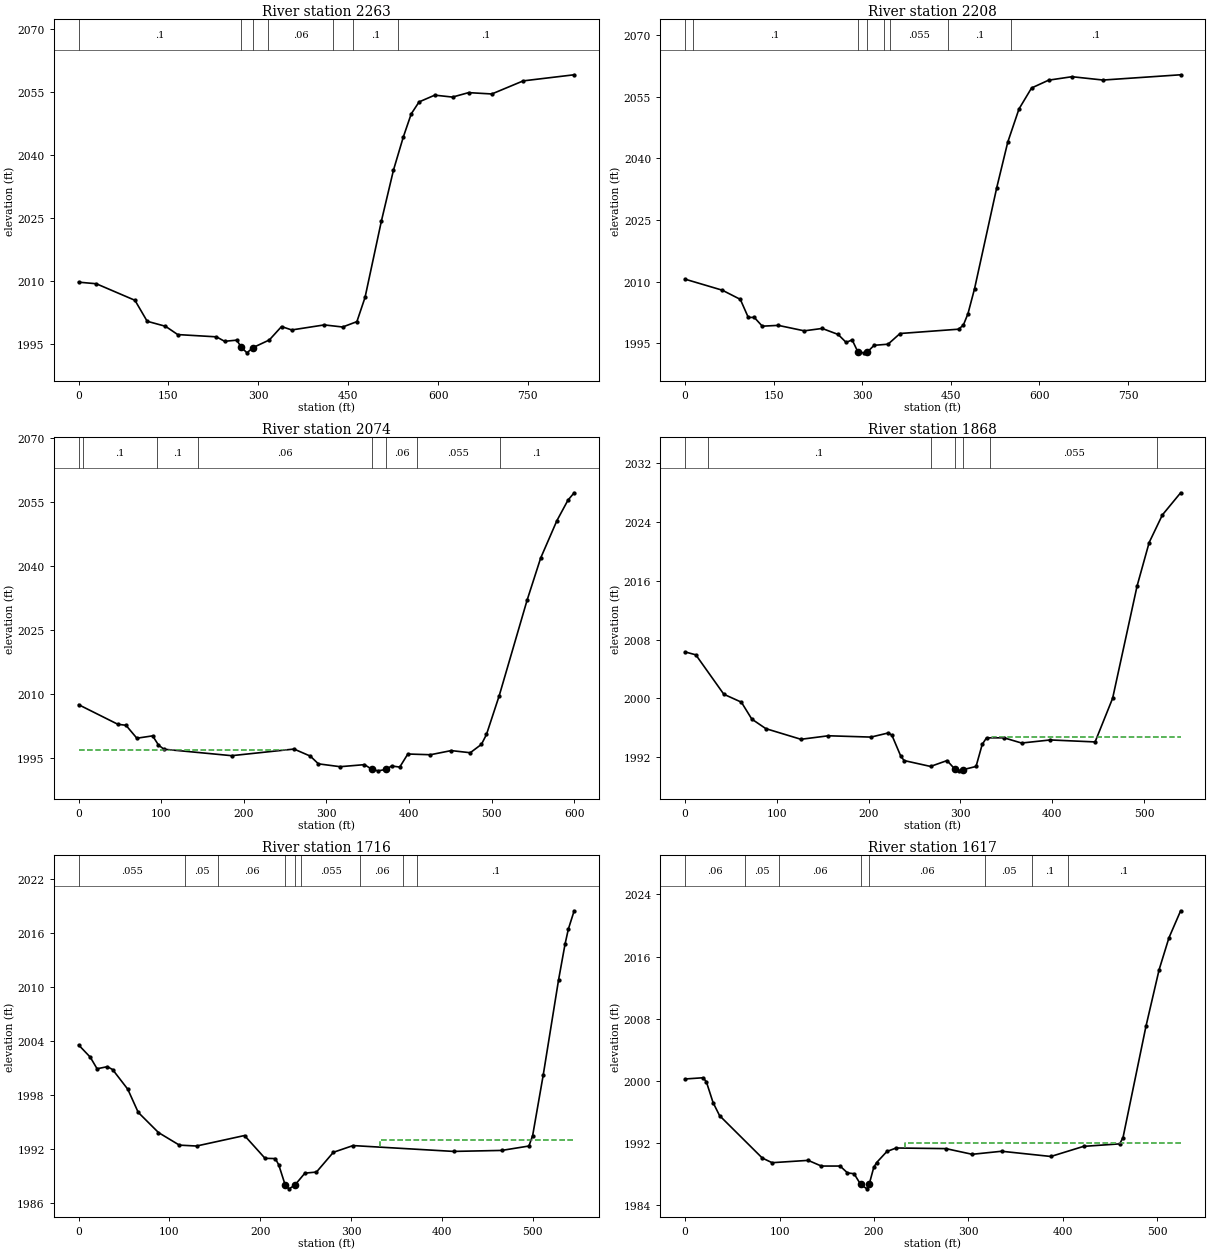
Type RM Length L Ch R = 1 ,2263    ,53.6,55,54.3
XS GIS Cut Line= 3
2208083.52993724341535.3187995682208590.51272397341672.315986423
2208892.46570724 341666.72426451
#Sta/Elev= 30
       0 2009.78    29.5  2009.4      94 2005.46   114.4 2000.47     145 1999.27
   165.4  1997.3     230 1996.76   243.6  1995.7     264 1995.97   271.6 1994.26
     281 1992.95   291.2 1994.21   318.3 1996.01   338.7 1999.21   355.7  1998.4
   410.1  1999.6   440.7  1999.1   464.5 2000.38   478.1 2006.15   505.3 2024.27
   525.6 2036.48     542 2044.35   555.2 2049.85   568.3  2052.7   594.5 2054.31
   624.1 2053.85     651 2054.91   689.7 2054.59   742.2 2057.71   827.2 2059.16
#Mann= 7 ,-1 , 0
       0      .1       0   271.6    .045       0   291.2      .1       0
  316.35     .06       0  425.36    .055       0  457.45      .1       0
  533.65      .1       0
Bank Sta=271.6,291.2
XS Rating Curve= 0 ,0
Exp/Cntr=0.3,0.1

Type RM Length L Ch R = 1 ,2208    ,135.7,133.8,132.1
XS GIS Cut Line= 3
2208070.48258611341589.3721113882208595.17249223341719.845622679
2208892.46570724341694.682874073
#Sta/Elev= 30
       0 2010.61      63 2007.93    93.5  2005.7     107  2001.3   117.1 2001.32
   130.7 1999.18   157.7 1999.38   201.7 1998.05   232.1 1998.63   259.1 1997.17
   272.7 1995.23   282.8 1995.86   292.4 1992.97   302.8  1992.7   308.7 1992.92
     320 1994.53   343.6  1994.8   363.9  1997.4     463 1998.45   471.1 1999.44
   478.9 2002.21   490.1 2008.31   527.7  2032.9   546.3 2043.93   565.3    2052
   586.6  2057.1   615.5    2059     655 2059.84   707.7 2059.03     839 2060.31
#Mann= 8 ,-1 , 0
       0     .06       0   12.85      .1       0   292.4    .045       0
   308.7      .1       0  336.98     .06       0  346.76    .055       0
  445.03      .1       0  552.12      .1       0
Bank Sta=292.4,308.7
XS Rating Curve= 0 ,0
Exp/Cntr=0.3,0.1

Type RM Length L Ch R = 1 ,2074    ,201.1,205.8,211.5
XS GIS Cut Line= 2
2208008.73468994341785.7300102972208608.55378285341800.462823205
#Sta/Elev= 30
       0 2007.45    47.5 2002.86    57.3 2002.63    70.5  1999.6    89.6 2000.15
    96.7    1998   103.3 1997.02   185.3 1995.51   260.8 1997.06   280.5 1995.41
   290.3  1993.6   316.6 1992.93   346.1 1993.41   355.21992.296   362.5 1991.96
   372.4  1992.3   378.9  1993.1   388.8 1992.84   398.6  1995.9     426 1995.73
   451.1  1996.7   474.2  1996.2   487.7 1998.16   493.8 2000.47   509.3 2009.59
     543 2031.92   559.4 2041.77   579.1 2050.55   592.5 2055.35     600 2057.07
#Mann= 8 ,-1 , 0
       0     .06       0    4.96      .1       0   95.43      .1       0
  145.13     .06       0   355.2    .045       0   372.4     .06       0
   409.2    .055       0  510.25      .1       0
#XS Ineff= 2 , 0
           255.3 1996.95
Permanent Ineff=
       F       F
Bank Sta=355.2,372.4
XS Rating Curve= 0 ,0
Exp/Cntr=0.3,0.1

Type RM Length L Ch R = 1 ,1868    ,152.3,152.6,151.7
XS GIS Cut Line= 2
 2207996.9747418341799.9936367572208461.08766053342075.851917771
#Sta/Elev= 30
       0 2006.31    11.7 2005.91    42.2 2000.54    61.3 1999.46    72.7 1997.15
      88 1995.85   126.2  1994.4   156.1 1994.88   202.5  1994.7   221.6 1995.27
   225.4 1994.93   235.1 1992.07   238.7  1991.5   267.4  1990.7   285.4  1991.5
   294.1 1990.31   297.9  1990.1   302.9 1990.26     317  1990.7   323.7  1993.7
   328.4  1994.6   347.5  1994.6   366.6 1993.89   397.9 1994.31   446.7 1994.04
   465.8 1999.99   492.5 2015.32   505.6 2021.22     520 2024.98   539.9    2028
#Mann= 7 ,-1 , 0
       0     .06       0   24.48      .1       0  267.55     .06       0
   294.1    .045       0   302.9     .06       0  332.46    .055       0
  514.38      .1       0
#XS Ineff= 2 , 0
                          334.06         1994.66
Permanent Ineff=
       F       F
Bank Sta=294.1,302.9
XS Rating Curve= 0 ,0
Exp/Cntr=0.3,0.1

Type RM Length L Ch R = 1 ,1716    ,100.1,99.3,98.2
XS GIS Cut Line= 2
2207946.64924459341944.4464528282208421.01365349342213.781058278
#Sta/Elev= 30
       0 2003.56    12.8  2002.2    20.3 2000.91    31.7 2001.14    37.4 2000.82
    54.1 1998.63    65.6 1996.05    87.9  1993.8   110.9  1992.4   129.8  1992.3
   182.6 1993.47   205.2 1990.93   216.5  1990.9   220.3  1990.2   227.5 1987.92
   231.6 1987.53   237.9 1987.93   249.1 1989.28   261.8  1989.4   280.4  1991.6
   302.1 1992.35   412.7  1991.7   465.7 1991.81   495.7  1992.3   499.8 1993.47
   511.4 2000.19   528.3  2010.8   535.5 2014.82   539.1 2016.47   545.5 2018.51
#Mann= 9 ,-1 , 0
       0    .055       0   117.5     .05       0  153.16     .06       0
   227.5    .045       0   237.9     .06       0  244.96    .055       0
  310.02     .06       0  357.22      .1       0  372.42      .1       0
#XS Ineff= 2 , 0
                          332.09         1993.02
Permanent Ineff=
       F       F
Bank Sta=227.5,237.9
XS Rating Curve= 0 ,0
Exp/Cntr=0.3,0.1

Type RM Length L Ch R = 1 ,1617    ,178.7,176.8,176.2
XS GIS Cut Line= 2
2207936.39775441  342088.89926892208432.09059902342260.686043018
#Sta/Elev= 30
       0 2000.26    19.2 2000.42    22.6 1999.87    29.6 1997.23    36.5 1995.55
    81.7  1990.1    92.1  1989.5   130.3  1989.8   144.2 1989.07   164.1 1989.07
   171.9 1988.19   178.9 1988.08   185.8 1986.72   192.4 1986.14     195 1986.78
   199.7 1988.89   202.7 1989.51   213.6 1990.94   223.4 1991.39   276.1 1991.31
   303.9 1990.58   335.1 1990.97   387.2  1990.3   421.9  1991.6   460.1 1991.92
   463.6 1992.73   487.9 2007.04   501.8  2014.3   512.2  2018.4   524.6 2021.88
#Mann= 8 ,-1 , 0
       0     .06       0   63.08     .05       0    99.9     .06       0
   185.8    .045       0     195     .06       0  317.94     .05       0
   367.5      .1       0  405.15      .1       0
#XS Ineff= 2 , 0
                          233.26         1992.09
Permanent Ineff=
       F       F
Bank Sta=185.8,195
XS Rating Curve= 0 ,0
Exp/Cntr=0.3,0.1

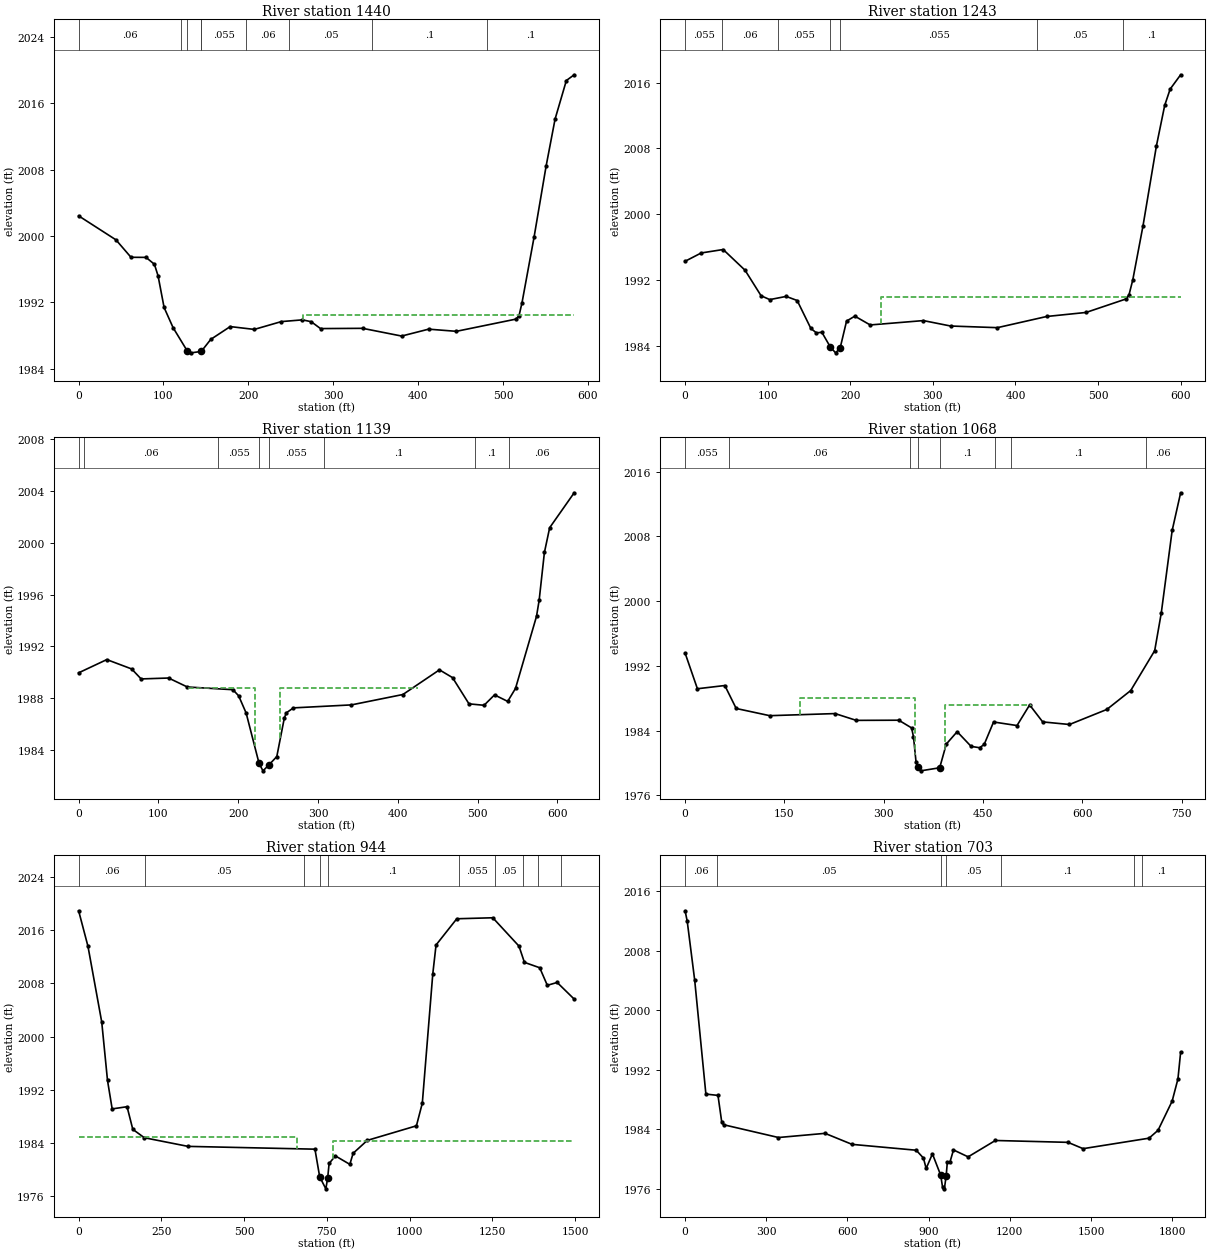
Type RM Length L Ch R = 1 ,1440    ,199.3,196.7,194.9
XS GIS Cut Line= 2
2207871.16099877342228.6923167112208411.69411697342449.565332254
#Sta/Elev= 30
       0 2002.43      44 1999.54    61.7 1997.44    79.4 1997.43    89.3  1996.6
    93.6 1995.21   100.7  1991.4   111.3 1988.97   128.1 1986.15   132.6 1985.94
   144.5 1986.11   155.7 1987.56   178.6  1989.1     207 1988.76   238.8  1989.7
   263.7 1989.91     274 1989.69     285 1988.86   334.6 1988.89   380.6 1987.96
   412.4 1988.79   445.1 1988.53   515.3    1990   518.9  1990.4   522.4 1991.95
   536.6 1999.84   550.8  2008.4   561.4 2014.08   574.7 2018.72   583.9 2019.41
#Mann= 9 ,-1 , 0
       0     .06       0  121.09    .055       0   128.1    .045       0
   144.5    .055       0  144.53    .055       0  197.75     .06       0
  248.03     .05       0  345.77      .1       0  480.86      .1       0
#XS Ineff= 2 , 0
                          263.97         1990.47
Permanent Ineff=
       F       F
Bank Sta=128.1,144.5
XS Rating Curve= 0 ,0
Exp/Cntr=0.3,0.1

Type RM Length L Ch R = 1 ,1243    ,101.5,103.8,105.9
XS GIS Cut Line= 2
2207810.56828893342442.9971763012208403.36568851342535.686134931
#Sta/Elev= 30
       0 1994.27    19.5 1995.28    46.1  1995.7    72.6 1993.18      92 1990.08
   102.5 1989.61   122.4    1990   135.7  1989.5   152.3  1986.1     159 1985.57
   165.6 1985.64   175.9 1983.84   182.2 1983.14   187.7 1983.71   195.5    1987
   205.5  1987.6   224.1 1986.53   288.5 1987.06   321.5  1986.4   378.1  1986.2
   437.9 1987.56   485.5 1988.05   534.2  1989.7   537.5  1990.2     542 1991.98
   554.4 1998.56   570.7 2008.31   580.7 2013.22   587.3  2015.2     600 2016.94
#Mann= 7 ,-1 , 0
       0    .055       0   44.63     .06       0  112.67    .055       0
   175.9    .045       0   187.7    .055       0  426.16     .05       0
  530.65      .1       0
#XS Ineff= 2 , 0
                          237.12         1989.94
Permanent Ineff=
       F       F
Bank Sta=175.9,187.7
XS Rating Curve= 0 ,0
Exp/Cntr=0.3,0.1

Type RM Length L Ch R = 1 ,1139    ,71.4,71.6,78.1
XS GIS Cut Line= 3
2207785.42126278342456.0890078182208173.11398204342686.281559881
2208342.72954672342697.465003706
#Sta/Elev= 30
       0 1989.97    35.3 1990.99    66.4 1990.27    78.3  1989.5   112.7 1989.57
   136.2 1988.88   193.3 1988.67   200.5  1988.2   209.9 1986.87   226.1 1982.99
     231 1982.42     238 1982.85   248.3 1983.52   257.7 1986.48   260.3 1986.89
   269.1 1987.27   341.8  1987.5   406.3  1988.3   452.1  1990.2   468.5  1989.6
   489.1 1987.58     508 1987.47   521.1 1988.27   537.6 1987.77   547.4 1988.77
   573.7 1994.32     577 1995.55   583.6 1999.24   590.2 2001.15   620.9 2003.84
#Mann= 8 ,-1 , 0
       0    .055       0    7.12     .06       0  174.69    .055       0
   226.1    .045       0     238    .055       0  306.93      .1       0
  496.48      .1       0  539.23     .06       0
#XS Ineff= 2 ,-1
  136.61   220.5 1988.83  252.72  424.761988.799
Permanent Ineff=
       F       F
Bank Sta=226.1,238
XS Rating Curve= 0 ,0
Exp/Cntr=0.3,0.1

Type RM Length L Ch R = 1 ,1068    ,123.7,123.9,108
XS GIS Cut Line= 4
2207728.10611317 342402.967649652207767.72423675342524.447976421
2208155.41695601342754.6405284832208325.03252069342765.823972308
#Sta/Elev= 30
       0 1993.58    18.6 1989.17      60 1989.57    77.2 1986.73   127.8 1985.84
   226.6  1986.1   258.6 1985.26   322.8 1985.28   342.1 1984.33     345 1983.25
   348.8 1980.17   351.1  1979.5   355.9 1979.02   384.6  1979.4   394.6 1982.33
     411 1983.86   432.1 1982.04   444.9 1981.88   451.8 1982.28     466 1985.06
   501.4 1984.62   520.5 1987.17   540.2 1985.07   580.7 1984.75   637.1 1986.61
   673.2 1988.95   709.4 1993.88   719.3 1998.51   735.8 2008.74   748.6  2013.4
#Mann= 8 ,-1 , 0
       0    .055       0   66.69     .06       0  339.28      .1       0
   351.1    .045       0   384.6      .1       0  468.88      .1       0
  492.38      .1       0  696.01     .06       0
#XS Ineff= 2 ,-1
  173.32  347.79 1988.01  392.17  522.26 1987.21
Permanent Ineff=
       F       F
Bank Sta=351.1,384.6
XS Rating Curve= 0 ,0
Exp/Cntr=0.3,0.1

Type RM Length L Ch R = 1 ,944     ,238.7,240.8,244.3
XS GIS Cut Line= 3
2207593.32231624342246.3994361022207765.60078667 342741.27243203
2208734.03358638 342833.53023691
#Sta/Elev= 30
       0  2018.9    28.2 2013.56    69.8 2002.18    87.2 1993.41   101.3 1989.13
   146.3 1989.46   163.6 1986.06   198.4  1984.8   330.3  1983.5   713.8 1983.08
   728.1 1978.93   746.7 1977.12   752.2 1978.74   756.6 1980.93   775.4 1982.07
   819.2  1980.8   829.1 1982.46   871.9  1984.4  1020.3 1986.59  1038.1 1989.99
  1069.7  2009.4  1079.6 2013.76  1142.2  2017.7    1251 2017.85  1330.1 2013.59
  1346.5 2011.15  1392.7 2010.34  1415.7  2007.7  1445.4 2008.13  1496.8 2005.63
#Mann= 10 ,-1 , 0
       0     .06       0  199.99     .05       0  679.26      .1       0
   728.1    .045       0   752.2      .1       0 1147.95    .055       0
 1256.64     .05       0 1341.16    .055       0 1388.33      .1       0
 1457.62     .06       0
#XS Ineff= 2 , 0
          658.65 1984.92  767.26         1984.36
Permanent Ineff=
       F       F
Bank Sta=728.1,752.2
XS Rating Curve= 0 ,0
Exp/Cntr=0.3,0.1

Type RM Length L Ch R = 1 ,703     ,280.4,281.4,275.4
XS GIS Cut Line= 4
2207548.10264763 342229.317146452207778.12182357342957.612468585
2208406.29869533343102.8557234982208779.46787284 342903.94636255
#Sta/Elev= 30
       0 2013.38     7.9 2011.96    35.5 2004.04    76.8 1988.74   121.5 1988.56
   135.2 1985.03   142.1 1984.62   345.1  1982.9   517.2 1983.46   616.9 1981.98
   854.2 1981.19   880.8 1980.14   890.9 1978.74   914.1  1980.7   944.5 1977.85
   951.5 1976.24   958.2    1976     965 1977.79   969.1 1979.57   978.5 1979.55
   991.9 1981.23    1046  1980.3  1146.7  1982.5  1415.1 1982.25  1470.9  1981.4
  1714.6 1982.81  1747.9 1983.87    1800 1987.79  1821.4 1990.77  1831.4 1994.37
#Mann= 7 ,-1 , 0
       0     .06       0   116.5     .05       0   944.5    .045       0
     965     .05       0  1169.1      .1       0    1658    .055       0
  1688.6      .1       0
Bank Sta=944.5,965
XS Rating Curve= 0 ,0
Exp/Cntr=0.3,0.1