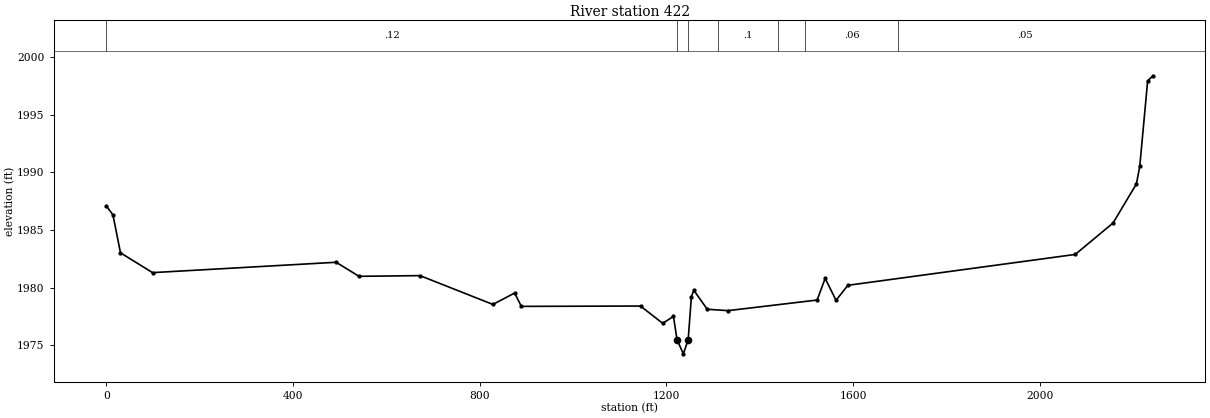
HEC-RAS study WILEYRN.prj: WILEYRN

--- WILEYRN.g02 (geometry) --- (continued)

Type RM Length L Ch R = 1 ,422     ,228.7,228.7,228.7
XS GIS Cut Line= 4
2207462.12308636 342255.634790222207708.92243936 343201.79288772
2208163.48229816343330.2720562682208837.07231079342912.843024351
#Sta/Elev= 30
       0 1987.11    14.5 1986.31    30.6 1983.02    99.3  1981.3   492.6  1982.2
   541.5 1980.98   672.3 1981.04   828.3 1978.54     875 1979.53   889.3 1978.37
  1144.6  1978.4  1192.1  1976.9  1215.2  1977.5  1222.8 1975.48  1236.4 1974.25
  1246.7 1975.47  1253.6 1979.22  1258.9 1979.76  1287.6 1978.12  1331.9    1978
    1523 1978.92  1540.1  1980.8  1563.5  1978.9  1588.8  1980.2  2075.9 1982.88
  2156.9 1985.61  2206.9    1989  2214.1 1990.53    2231 1997.96  2242.6 1998.39
#Mann= 7 ,-1 , 0
       0     .12       0  1222.8    .045       0  1246.7     .12       0
 1309.62      .1       0  1439.1    .055       0  1497.4     .06       0
  1695.4     .05       0
Bank Sta=1222.8,1246.7
XS Rating Curve= 0 ,0
Exp/Cntr=0.3,0.1
LCMann Table=0

Chan Stop Cuts=-1
Use User Specified Reach Order=0
Composite Channel Slope=5